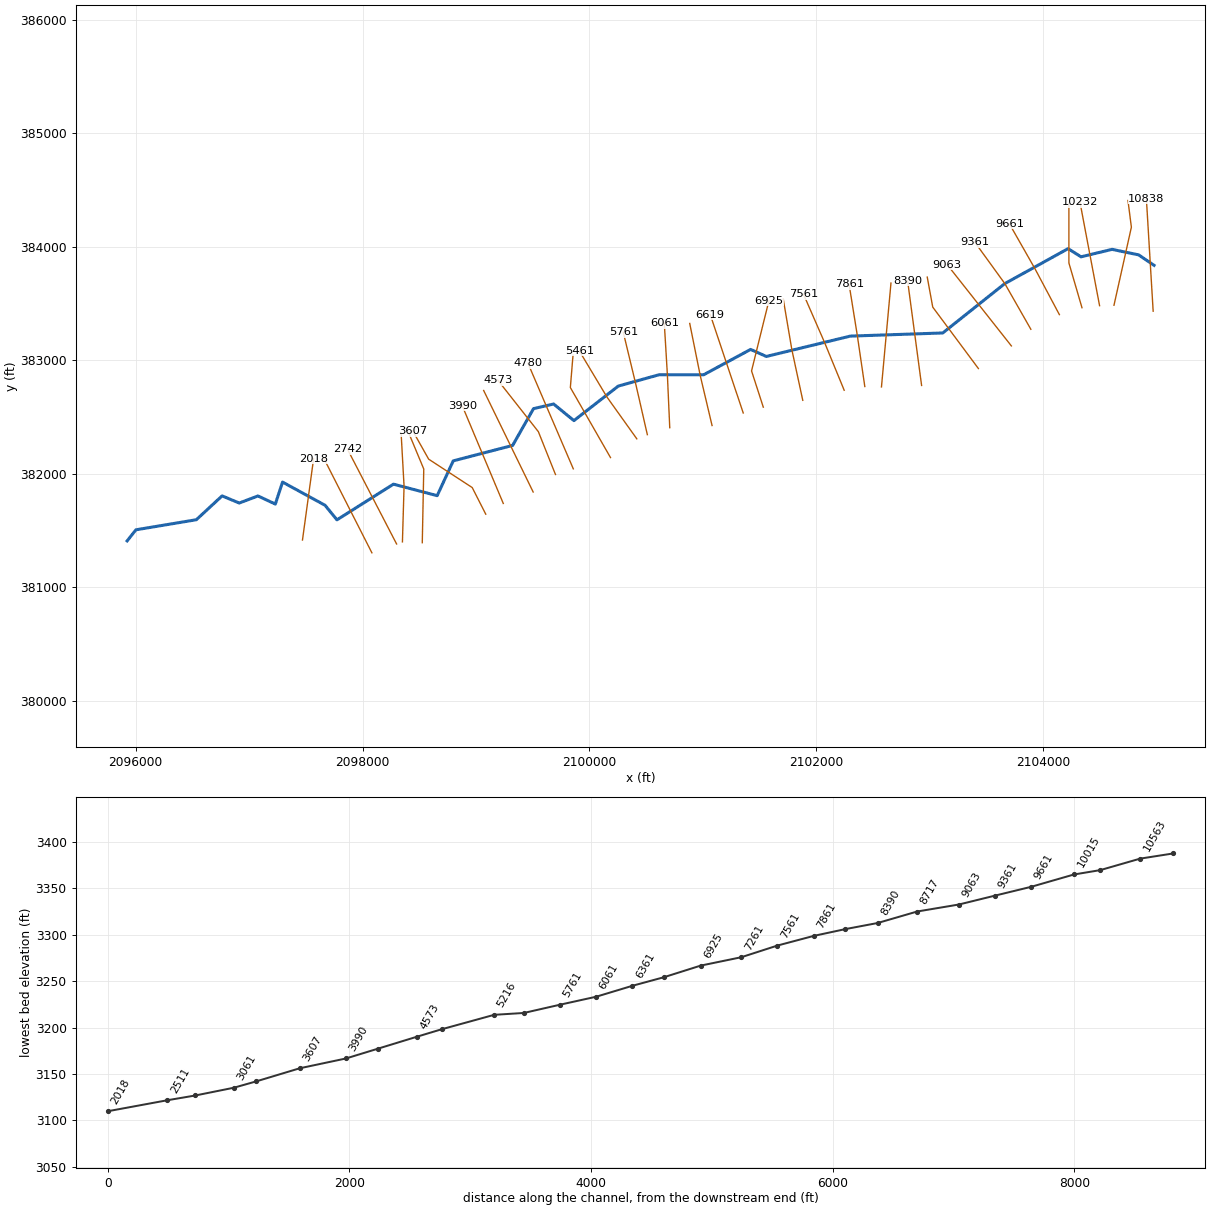
--- OLFLDBR.prj (project) ---

Proj Title=OLFLDBR
Current Plan=p01
Default Exp/Contr=0,0
English Units
Geom File=g01
Flow File=f01
Plan File=p01
BEGIN DESCRIPTION:
Stream Name- Old Field Branch
Flood Zone: Zone A
Greenbrier County, WV
County-Wide Study
WVDHSEM-2018-3, Flood Risk Project
HEC-RAS Version: 5.0.7
General Notes:
For the Hydrology regression was used.
END DESCRIPTION:
DSS Export Rating Curves= 0
DSS Export Rating Curve Sorted= 0
DSS Export Volume Flow Curves= 0
DXF OffsetX= 0
DXF OffsetY= 0
DXF ScaleX= 0
DXF ScaleY= 0

--- OLFLDBR.p01 (plan) ---

Plan Title=Floodplain
Program Version=5.07
Short Identifier=Floodplain
Geom File=g01
Flow File=f01
Subcritical Flow
K Sum by GR= 0
Std Step Tol= 0.01
Critical Tol= 0.01
Num of Std Step Trials= 20
Max Error Tol= 0.3
Flow Tol Ratio= 0.001
Split Flow NTrial= 30
Split Flow Tol= 0.02
Split Flow Ratio= 0.02
Log Output Level= 0
Friction Slope Method= 1
Unsteady Friction Slope Method= 2
Unsteady Bridges Friction Slope Method= 1
Parabolic Critical Depth
Global Vel Dist= 0 , 0 , 0
Global Log Level= 0
CheckData=True
Encroach Param=-1 ,0,0, 0
Mapping Interval=1HOUR
Computation Time Step Use Courant=        0
Computation Time Step Use Time Series=    0
Computation Time Step Count To Double=0
Computation Time Step Max Doubling=0
Computation Time Step Max Halving=0
Computation Time Step Residence Courant=0
Run HTab= 0
Run UNet= 0
Run Sediment= 0
Run PostProcess= 0
Run WQNet= 0
Run RASMapper=-1
UNET Theta= 0
UNET Theta Warmup= 0
UNET ZTol= 0
UNET ZSATol= 0
UNET MxIter= 0
UNET Max Iter WO Improvement= 0
UNET MaxInSteps= 0
UNET DtIC= 0
UNET DtMin= 0
UNET MaxCRTS= 0
UNET WFStab= 0
UNET SFStab= 0
UNET WFX= 1
UNET SFX= 1
UNET 1D Methodology=Finite Difference
UNET DSS MLevel= 1
UNET Pardiso=0
UNET DZMax Abort= 0
UNET Use Existing IB Tables= 0
UNET Froude Reduction=False
UNET Froude Limit= 0
UNET Froude Power= 0
UNET D1 Cores= 0
UNET D2 Coriolis=0
UNET D2 Cores= 0
UNET D2 Theta= 1
UNET D2 Theta Warmup= 1
UNET D2 Z Tol= 0.01
UNET D2 Volume Tol= 0.01
UNET D2 Max Iterations= 20
UNET D2 Equation= 0
UNET D2 RampUpFraction=0.1
UNET D2 TimeSlices= 1
UNET D2 BCVolumeCheck=0
UNET D1D2 MaxIter= 0
UNET D1D2 ZTol=0.01
UNET D1D2 QTol=0.1
UNET D1D2 MinQTol=1
Write IC File= 0
Write IC File at Fixed DateTime=0
Write IC File at Sim End=0
Echo Input=False
Echo Parameters=False
Echo Output=False
Write Detailed= 0
HDF Write Warmup=0
HDF Write Time Slices=0
HDF Flush=0
HDF Face Node Velocities=0
HDF Compression= 1
HDF Chunk Size= 1
HDF Spatial Parts= 1
HDF Use Max Rows=0
HDF Fixed Rows= 1
Calibration Method= 0
Calibration Iterations= 20
Calibration Max Change=0.05
Calibration Tolerance=0.2
Calibration Maximum=1.5
Calibration Minimum=0.5
Calibration Optimization Method= 1
WQ AD Non Conservative
WQ ULTIMATE=-1
WQ Max Comp Step=1HOUR
WQ Output Interval=15MIN
WQ Output Selected Increments= 0
WQ Output face flow=0
WQ Output face velocity=0
WQ Output face area=0
WQ Output face dispersion=0
WQ Output cell volume=0
WQ Output cell surface area=0
WQ Output cell continuity=0
WQ Output cumulative cell continuity=0
WQ Output face conc=0
WQ Output face dconc_dx=0
WQ Output face courant=0
WQ Output face peclet=0
WQ Output face adv mass=0
WQ Output face disp mass=0
WQ Output cell mass=0
WQ Output cell source sink temp=0
WQ Output nsm pathways=0
WQ Output nsm derived pathways=0
WQ Output MaxMinRange=-1
WQ Daily Max Min Mean=-1
WQ Daily Range=0
WQ Daily Time=0
WQ Create Restart=0
WQ Fixed Restart=0
WQ System Summary=0
WQ Write To DSS=0
WQ Use Fixed Temperature=0
Sorting and Armoring Iterations= 10
XS Update Threshold= 0.02
Bed Roughness Predictor= 0
Hydraulics Update Threshold= 0.02
Energy Slope Method= 1
Volume Change Method= 1
Sediment Retention Method= 0
XS Weighting Method= 0
Number of US Weighted Cross Sections= 1
Number of DS Weighted Cross Sections= 1
Upstream XS Weight=0
Main XS Weight=1
Downstream XS Weight=0
Number of DS XS's Weighted with US Boundary= 1
Upstream Boundary Weight= 1
Weight of XSs Associated with US Boundary= 0
Number of US XS's Weighted with DS Boundary= 1
Downstream Boundary Weight= 0.5
Weight of XSs Associated with DS Boundary= 0.5
Percentile Method= 0
Sediment Output Level= 3
Mass or Volume Output= 0
Output Increment Type= 1
Profile and TS Output Increment= 1
XS Output Flag= 0
XS Output Increment= 10
Write Gradation File= 0
Read Gradation Hotstart= 0
Write HDF5 File= 1
Write Binary Output= 1
Write DSS Sediment File= 0
SV Curve= 0
Specific Gage Flag= 0

--- OLFLDBR.f01 (steady flow) ---

Flow Title=H3a_CombinedFlows
Program Version=5.07
Number of Profiles= 6
Profile Names=f1p,f10p,f4p,f2p,f02p,f1pplus
River Rch & RM=OLFLDBR,Main            ,10838
     549     290     386     465     768     812
River Rch & RM=OLFLDBR,Main            ,8122
     628     333     442     532     876     929
River Rch & RM=OLFLDBR,Main            ,7861
     704     375     497     597     979    1040
River Rch & RM=OLFLDBR,Main            ,6061
     804     431     569     683    1120    1190
River Rch & RM=OLFLDBR,Main            ,695
     896     482     635     761    1240    1320
River Rch & RM=OLFLDBR,Main            ,54
    1620     892    1160    1380    2220    2400
Boundary for River Rch & Prof#=OLFLDBR,Main            , 1
Up Type= 0
Dn Type= 1
Dn Known WS=3061.56
Boundary for River Rch & Prof#=OLFLDBR,Main            , 2
Up Type= 0
Dn Type= 1
Dn Known WS=3060.31
Boundary for River Rch & Prof#=OLFLDBR,Main            , 3
Up Type= 0
Dn Type= 1
Dn Known WS=3060.8
Boundary for River Rch & Prof#=OLFLDBR,Main            , 4
Up Type= 0
Dn Type= 1
Dn Known WS=3061.18
Boundary for River Rch & Prof#=OLFLDBR,Main            , 5
Up Type= 0
Dn Type= 1
Dn Known WS=3062.73
Boundary for River Rch & Prof#=OLFLDBR,Main            , 6
Up Type= 0
Dn Type= 1
Dn Known WS=3063.02
DSS Import GetInterval= 0
DSS Import GetPeak= 0
DSS Import FillOption= 0

--- OLFLDBR.g01 (geometry) ---

Geom Title=Geometry
Program Version=5.07

River Reach=OLFLDBR         ,Main
Reach XY= 30
2104977.34299999383836.2220000182104841.25200003383928.518999994
2104607.17199999383977.1100000142104333.53899999383911.283000007
2104219.64400002383983.5409999942103660.98300003383674.873000011
2103114.68300001383240.1380000112102299.53500001383212.408000022
2101559.12500001383033.0540000052101421.01499999383095.233999997
     2101006.741382871.503000006     2100614.727382872.002000004
     2100255.007382772.1470000152099863.33000004 382467.47300002
2099684.35300002382613.998000026     2099507.049382572.981000006
2099323.25800005382248.8949999962098799.62100004382112.813000023
     2098657.972381805.913000017     2098272.587 381907.32100001
2097774.65500003381592.8229999992097669.17200001381721.480000019
2097294.94400001381925.6940000062097231.40300003381731.855000004
2097078.37900002381803.3330000192096913.37100001381740.974000022
2096762.08000003381803.9329999982096535.13400002381593.824000016
2096002.62400001 381505.189000012095925.04552211381407.265366957

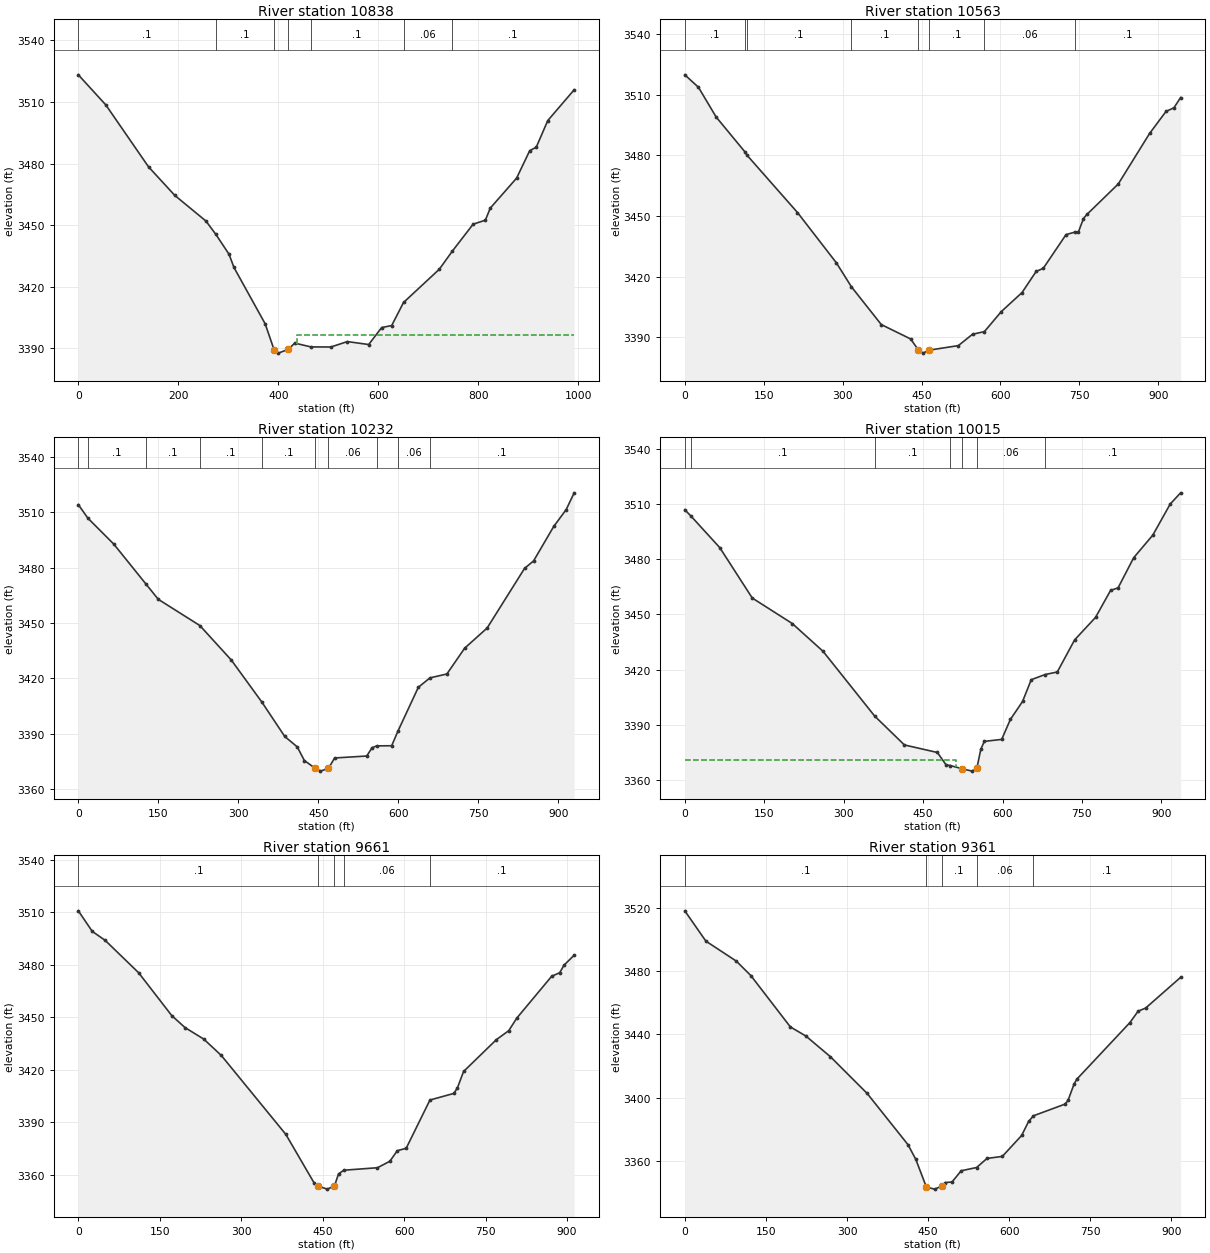
Type RM Length L Ch R = 1 ,10838   ,275.2,275.2,275.2
XS GIS Cut Line= 2
2104969.33369493383432.0109512852104909.64352272384421.994295246
#Sta/Elev= 30
       0  3523.2    55.1 3508.52   140.4 3478.42   192.9 3464.53   255.4    3452
  275.08 3445.55   301.4 3435.89   311.3 3429.44   373.7 3402.03     392 3389.07
     400 3387.74   419.7 3389.56   432.9 3392.61   465.3 3390.77   505.2 3390.72
   538.1 3393.36   580.8 3391.93   606.8 3400.19   626.8 3401.16  650.49 3412.39
   722.1 3428.58  748.06 3437.37   789.7  3450.5   814.2 3452.45     824 3458.32
   876.7 3472.93   902.9 3486.28     916 3487.98     939 3500.93   991.8 3515.92
#Mann= 7 ,-1 , 0
       0      .1       0  275.08      .1       0     392    .045       0
   419.7      .1       0   465.3      .1       0  650.49     .06       0
  748.06      .1       0
#XS Ineff= 2 , 0
                          437.84          3396.8
Permanent Ineff=
       F       F
Bank Sta=392,419.7
XS Rating Curve= 0 ,0
Exp/Cntr=0.3,0.1

Type RM Length L Ch R = 1 ,10563   ,330.8,330.8,330.8
XS GIS Cut Line= 3
2104624.02775611383484.5041379432104777.32958863384172.396976212
2104747.19333096384408.245949332
#Sta/Elev= 30
       0 3519.85    25.9 3513.71    59.5 3499.01  114.04  3481.8  118.08 3480.12
   214.2 3451.71   288.1 3426.82   316.8 3414.92   373.5 3396.26   429.3 3389.13
   443.4 3383.91   452.8 3382.12   464.2 3383.59     520 3385.84   546.9 3391.45
  569.48 3392.77   601.7 3402.69     641 3412.09   667.9 3422.55   681.4 3424.09
   724.7 3440.78  741.98 3442.04   747.9 3441.86   757.8 3448.72   764.4 3450.77
   823.9 3465.81   883.5 3490.83   914.7 3501.72   929.8 3503.55   942.5 3508.62
#Mann= 8 ,-1 , 0
       0      .1       0  114.04      .1       0  118.08      .1       0
   316.8      .1       0   443.4    .045       0   464.2      .1       0
  569.48     .06       0  741.98      .1       0
Bank Sta=443.4,464.2
XS Rating Curve= 0 ,0
Exp/Cntr=0.3,0.1

Type RM Length L Ch R = 1 ,10232   ,217.1,217.1,217.1
XS GIS Cut Line= 2
2104496.93136504383480.5733217252104323.97545141 384393.83295653
#Sta/Elev= 30
       0 3514.17   17.91 3506.82    66.5 3492.76  126.07 3471.38   149.9 3462.84
  227.78 3448.63   286.8 3429.92  344.12 3407.12     387 3388.49   410.4 3382.86
   423.7 3375.48   444.2 3371.21   453.8 3369.72   468.9 3371.23   480.5 3376.85
   540.6 3377.91   550.6 3382.38  559.34 3383.41   587.4 3383.48  599.26 3391.47
   637.4 3415.17  659.22 3420.27   690.9 3422.37   724.2 3436.34   766.4 3447.29
   836.5  3479.6   853.4 3483.64   891.2 3502.33   914.6 3511.48   929.5 3520.56
#Mann= 10 ,-1 , 0
       0      .1       0   17.91      .1       0  126.07      .1       0
  227.78      .1       0  344.12      .1       0   444.2    .045       0
   468.9     .06       0  559.34    .055       0  599.26     .06       0
  659.22      .1       0
Bank Sta=444.2,468.9
XS Rating Curve= 0 ,0
Exp/Cntr=0.3,0.1

Type RM Length L Ch R = 1 ,10015   ,354.2,354.2,354.2
XS GIS Cut Line= 3
2104341.90729779383462.6675366582104226.60335538383857.059430599
2104226.60335538384382.478531829
#Sta/Elev= 30
       0 3506.78   11.57 3503.39    66.2 3486.19   127.4 3458.91   202.9 3445.09
     261 3430.03  358.58 3394.87   414.7 3379.22     477 3375.13   493.4 3368.41
  501.35 3368.05     524 3366.28   542.6 3365.02   551.4 3366.46     559  3376.9
   565.6 3381.15   598.4 3382.23   614.8 3393.04   637.8 3402.79   654.2 3414.61
  680.57 3417.43   703.4 3418.79   736.2 3436.23   775.6 3448.39     804 3463.03
   818.2 3464.44   847.7 3480.79   883.8 3493.04   916.6 3509.88   936.3 3515.97
#Mann= 7 ,-1 , 0
       0      .1       0   11.57      .1       0  358.58      .1       0
  501.35     .06       0     524    .045       0   551.4     .06       0
  680.57      .1       0
#XS Ineff= 2 , 0
          512.94  3370.9
Permanent Ineff=
       F       F
Bank Sta=524,551.4
XS Rating Curve= 0 ,0
Exp/Cntr=0.3,0.1

Type RM Length L Ch R = 1 ,9661    ,300,300,300
XS GIS Cut Line= 3
     2104142.575      383401.848     2103928.281      383804.986
     2103702.258      384201.862
#Sta/Elev= 30
       0 3510.82    25.6 3499.09    49.4 3493.95   111.1 3475.42   172.1 3450.93
   196.5 3444.09   231.1 3437.49   263.4 3428.14   382.3    3383   434.3 3355.28
   441.8 3353.45   458.4 3351.74   471.7 3353.48   479.3 3360.47  488.94 3362.55
     551 3363.97   573.9 3367.69   587.5 3373.71   603.9 3375.09  647.67 3402.68
   691.7 3406.45   698.3 3409.63   709.6 3418.98     770 3437.17   792.8 3442.31
   807.8 3449.56   871.9 3473.42   886.6 3475.43   894.6 3479.74   913.3 3485.47
#Mann= 5 ,-1 , 0
       0      .1       0   441.8    .045       0   471.7      .1       0
  488.94     .06       0  647.67      .1       0
Bank Sta=441.8,471.7
XS Rating Curve= 0 ,0
Exp/Cntr=0.3,0.1

Type RM Length L Ch R = 1 ,9361    ,298.2,298.2,298.2
XS GIS Cut Line= 3
     2103891.304      383272.524     2103661.744      383675.377
     2103395.756      384042.558
#Sta/Elev= 30
       0 3518.04      39  3498.9    95.2 3486.29   122.2 3477.13   195.3 3444.68
     224 3438.94   269.3 3425.88   337.3 3402.68   412.8 3370.31   427.3 3361.01
   446.8 3343.53   461.9 3342.22   475.5 3344.09     482 3346.38   494.3 3346.74
   511.2 3353.82  539.72 3355.88     559 3361.62   587.3 3362.89   623.1 3376.15
   635.9 3384.96  644.94 3388.56   703.4 3395.94   708.9 3398.31   719.8 3408.42
   725.1 3411.68   823.2 3447.39   838.5 3454.65   852.4 3456.61   917.1 3476.03
#Mann= 5 ,-1 , 0
       0      .1       0   446.8    .045       0   475.5      .1       0
  539.72     .06       0  644.94      .1       0
Bank Sta=446.8,475.5
XS Rating Curve= 0 ,0
Exp/Cntr=0.3,0.1

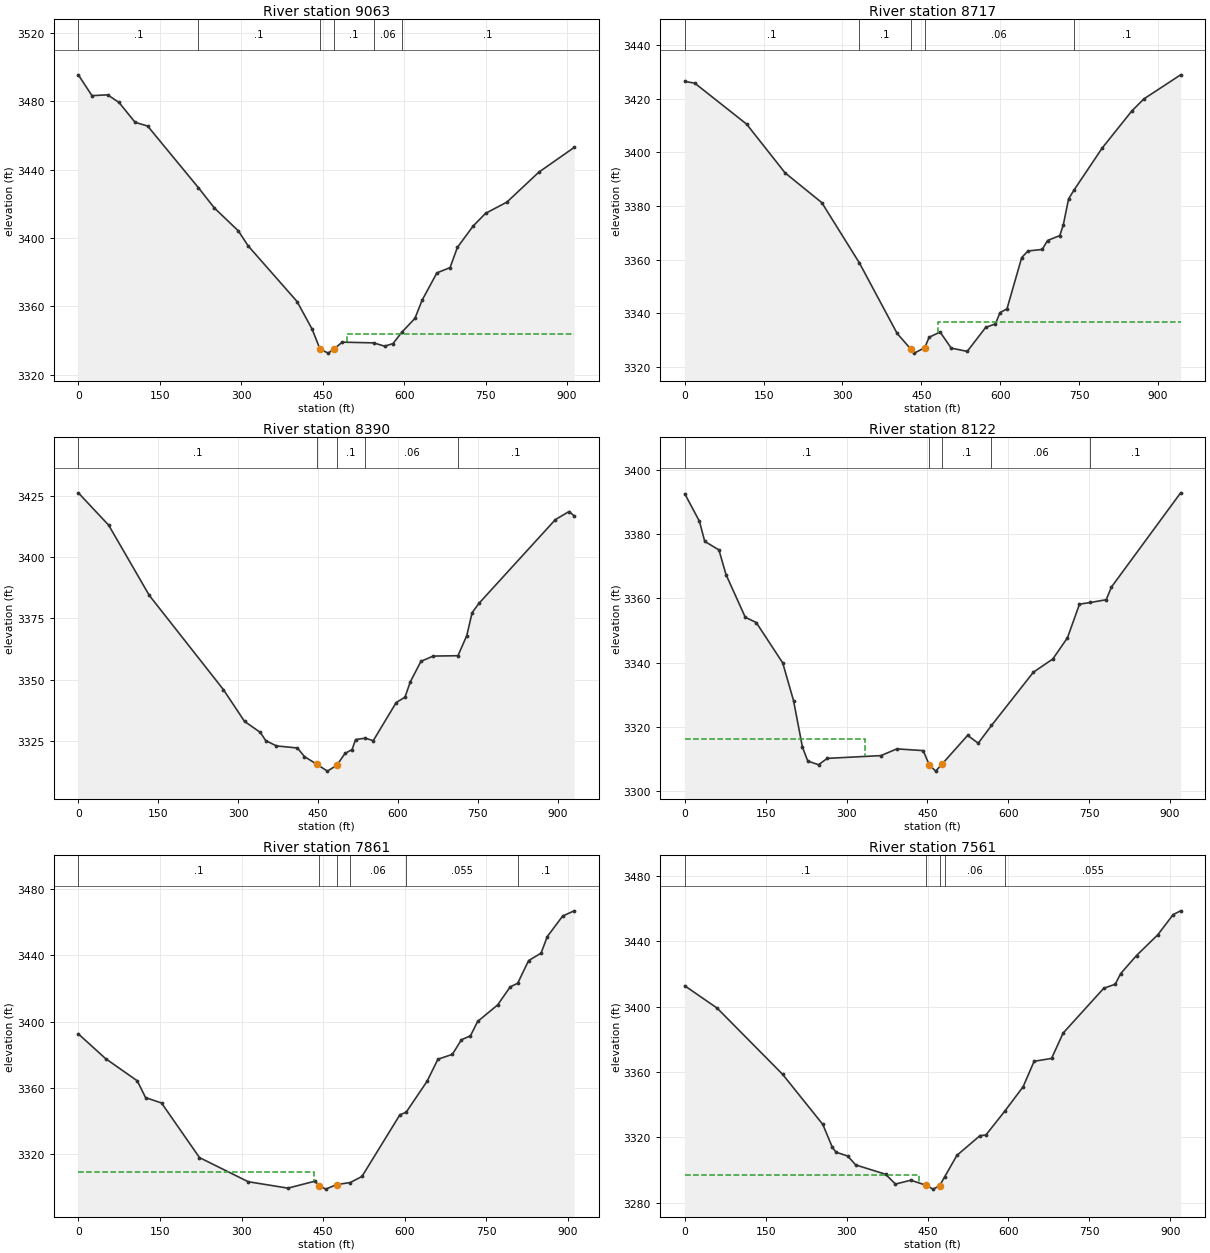
Type RM Length L Ch R = 1 ,9063    ,345.2,345.2,345.2
XS GIS Cut Line= 2
2103719.52806317383125.9276139252103153.49052768383842.646437797
#Sta/Elev= 30
       0 3495.55    25.1 3483.36      54 3483.84      75 3479.36   104.5 3467.77
   127.7 3465.56  221.07 3429.53   250.8 3417.54   294.6 3404.26   312.9  3395.4
   402.9 3362.86   430.6 3346.71   445.3  3334.9   460.4 3332.65   471.7 3335.26
   486.1 3339.08  543.83 3338.65   564.4 3336.72   579.6 3338.25  595.99 3344.92
     620    3353   633.3 3363.68   660.5 3379.63   684.7  3382.7   698.2 3394.52
   727.4 3407.12   750.1 3414.47   789.4 3421.05   848.2 3438.57   913.3 3453.04
#Mann= 6 ,-1 , 0
       0      .1       0  221.07      .1       0   445.3    .045       0
   471.7      .1       0  543.83     .06       0  595.99      .1       0
#XS Ineff= 2 , 0
                          494.27         3343.83
Permanent Ineff=
       F       F
Bank Sta=445.3,471.7
XS Rating Curve= 0 ,0
Exp/Cntr=0.3,0.1

Type RM Length L Ch R = 1 ,8717    ,327.2,327.2,327.2
XS GIS Cut Line= 3
2103428.64766299382926.7662588452103026.39413661 383467.90862495
2102977.91406991383732.583583674
#Sta/Elev= 30
       0 3426.52      19 3425.84   117.6 3410.57   190.9 3392.36   260.7 3381.26
  332.32 3358.73     404 3332.46   429.5 3326.74   436.5 3325.11   456.6 3327.13
   464.8 3331.03   485.8 3332.97   506.9 3326.99   537.4 3325.76   572.5 3334.72
     591 3336.01   599.7 3340.22     613 3341.63     641 3360.75   652.9 3363.23
   680.1  3363.8   690.2 3367.13   713.5 3368.98   720.2 3372.99   730.2 3382.65
  740.11 3385.83   794.4 3401.71   850.8 3415.53   873.6 3419.99   943.4 3428.96
#Mann= 5 ,-1 , 0
       0      .1       0  332.32      .1       0   429.5    .045       0
   456.6     .06       0  740.11      .1       0
#XS Ineff= 2 , 0
                          482.33         3336.81
Permanent Ineff=
       F       F
Bank Sta=429.5,456.6
XS Rating Curve= 0 ,0
Exp/Cntr=0.3,0.1

Type RM Length L Ch R = 1 ,8390    ,268.2,268.2,268.2
XS GIS Cut Line= 2
2102928.12373114382777.3952425352102804.95815629383699.826781852
#Sta/Elev= 30
       0 3426.24      57 3413.03   133.2  3384.4   272.2    3346   311.9 3333.02
   341.7  3328.5   351.6  3325.2   371.8 3323.01   411.2 3322.16   424.4 3318.66
   447.6 3315.51   467.5 3312.72   485.1 3315.11   500.6 3319.95   513.8 3321.54
   520.4 3325.61  538.77 3326.17   553.5 3325.13   596.6  3340.7   613.1  3342.9
     623 3349.11     643  3357.5   666.1 3359.65   712.5  3359.8     729 3367.96
   739.1 3377.37   752.1  3381.2   895.2 3415.29   920.9 3418.61   930.6 3416.86
#Mann= 5 ,-1 , 0
       0      .1       0   447.6    .045       0   485.1      .1       0
  538.77     .06       0   712.5      .1       0
Bank Sta=447.6,485.1
XS Rating Curve= 0 ,0
Exp/Cntr=0.3,0.1

Type RM Length L Ch R = 1 ,8122    ,261.1,261.1,261.1
XS GIS Cut Line= 2
2102574.35027146382764.2925218062102658.20768412383680.172700758
#Sta/Elev= 30
       0 3392.62    27.1 3384.07      37 3377.79    63.3 3375.12    76.5  3367.4
   112.2 3354.11   132.5 3352.48   181.6 3339.89   201.7 3328.11   218.2 3313.62
   228.1 3309.26     248 3308.12   264.3  3310.1   363.7 3310.96   393.4 3313.06
   442.2 3312.52   453.2 3308.15   465.3 3306.12   477.4 3308.36   524.6 3317.27
   544.3 3314.84  568.87 3320.36   646.6 3336.98   682.7 3341.11   709.8 3347.72
   732.1  3358.2  752.22 3358.72   781.6 3359.58   791.4 3363.55   919.7 3392.93
#Mann= 5 ,-1 , 0
       0      .1       0   453.2    .045       0   477.4      .1       0
  568.87     .06       0  752.22      .1       0
#XS Ineff= 2 , 0
           335.1 3316.19
Permanent Ineff=
       F       F
Bank Sta=453.2,477.4
XS Rating Curve= 0 ,0
Exp/Cntr=0.3,0.1

Type RM Length L Ch R = 1 ,7861    ,300,300,300
XS GIS Cut Line= 3
      2102427.55      382767.916     2102361.317      383218.756
     2102289.117      383668.435
#Sta/Elev= 30
       0 3392.59    50.1 3377.66   108.3 3364.25   123.6 3354.09   152.9 3350.85
   222.6 3317.88   312.1 3303.29   385.1 3299.41     435 3303.63   442.3 3300.89
   454.7 3298.81   474.6 3301.57  499.78 3302.81   521.2 3306.48   590.9 3343.73
   602.3 3345.23   640.8 3363.96   660.7 3377.27   687.3 3380.24   703.9 3389.05
   720.5 3391.43   733.8 3400.14   770.4 3410.06   793.6 3421.01  807.34 3423.19
   827.4  3436.9   850.3 3441.39   861.7 3451.38     890 3463.82   911.1 3466.95
#Mann= 6 ,-1 , 0
       0      .1       0   442.3    .045       0   474.6      .1       0
  499.78     .06       0   602.3    .055       0  807.34      .1       0
#XS Ineff= 2 , 0
          433.43 3309.05
Permanent Ineff=
       F       F
Bank Sta=442.3,474.6
XS Rating Curve= 0 ,0
Exp/Cntr=0.3,0.1

Type RM Length L Ch R = 1 ,7561    ,300,300,300
XS GIS Cut Line= 3
     2102245.824      382735.066     2102070.631      383161.431
     2101887.262      383581.453
#Sta/Elev= 30
       0 3412.73    59.8 3399.13   181.4  3358.6   255.9 3327.97   273.6 3313.95
   280.7 3310.95     302 3308.67   316.9 3303.22   372.2 3297.51   390.6 3291.51
     419 3293.87   447.7 3290.75   460.2 3288.42   472.3 3290.43  481.73 3295.89
   504.5 3309.07   547.4 3321.14   558.2 3321.48  594.01 3336.41   627.2 3350.99
   647.7 3366.59     680 3368.33   701.4 3383.82   776.7  3411.2   798.1 3413.72
   808.1 3420.18   837.5 3431.25   876.9 3443.91   905.5 3456.28   919.3 3458.57
#Mann= 5 ,-1 , 0
       0      .1       0   447.7    .045       0   472.3      .1       0
  481.73     .06       0  594.01    .055       0
#XS Ineff= 2 , 0
          434.61 3297.16
Permanent Ineff=
       F       F
Bank Sta=447.7,472.3
XS Rating Curve= 0 ,0
Exp/Cntr=0.3,0.1

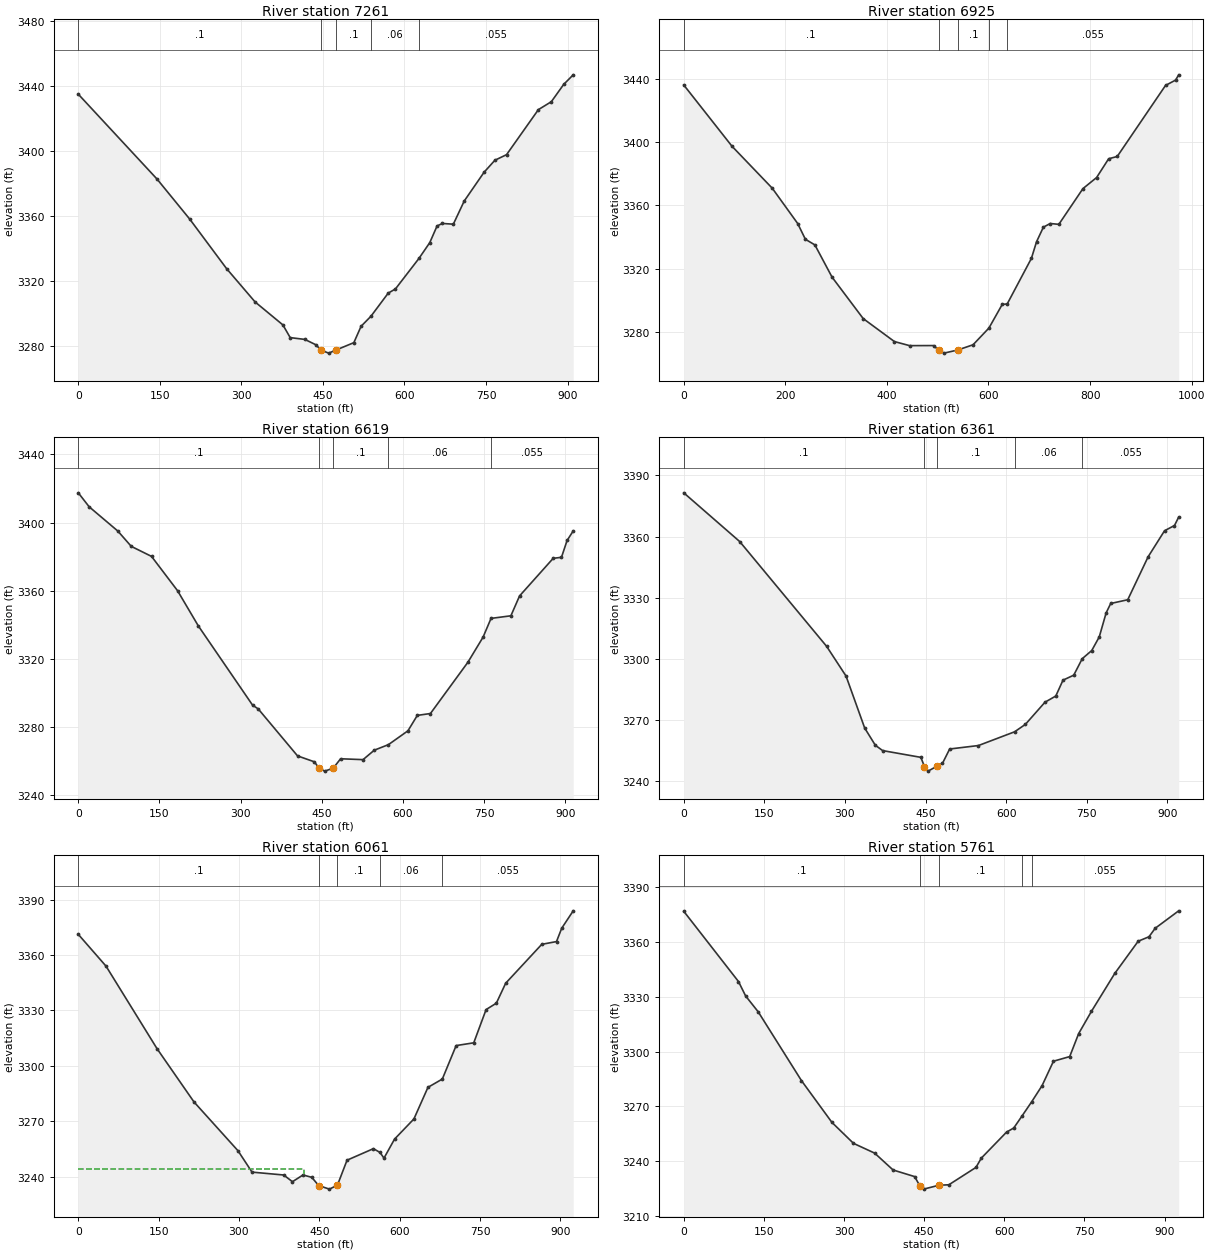
Type RM Length L Ch R = 1 ,7261    ,335.6,335.6,335.6
XS GIS Cut Line= 3
     2101880.674      382646.411     2101784.668      383091.555
     2101708.462      383540.105
#Sta/Elev= 30
       0 3434.78   144.8 3382.69   205.3 3357.95   272.7 3327.72   325.2 3307.24
   376.4 3293.11   389.8 3285.33   416.7 3284.22   436.8 3280.97   446.9 3277.58
   460.6  3275.8   473.6 3277.63   506.9 3282.23   520.2 3292.28  538.37 3298.45
   570.1 3312.64   583.4 3315.21   626.7 3333.97   646.6 3343.67     660 3353.91
   669.9 3355.41   689.9 3354.97   709.9 3369.18   746.5 3386.89   766.4 3394.24
   787.8 3397.65   846.3 3425.29   870.2 3430.18     893 3440.84   910.4 3446.67
#Mann= 5 ,-1 , 0
       0      .1       0   446.9    .045       0   473.6      .1       0
  538.37     .06       0   626.7    .055       0
Bank Sta=446.9,473.6
XS Rating Curve= 0 ,0
Exp/Cntr=0.3,0.1

Type RM Length L Ch R = 1 ,6925    ,306.3,306.3,306.3
XS GIS Cut Line= 3
2101532.68397351382586.0955198932101429.17247975382905.801905679
2101582.47431228383525.560596157
#Sta/Elev= 30
       0    3436      95 3397.33   174.3 3370.83   224.3 3348.58   239.5 3338.63
   258.2 3335.07     292 3314.73   353.3 3288.58   414.8 3274.07   444.6 3271.51
   491.8 3271.55     502 3268.61   512.4 3266.78   539.5 3268.76   569.6 3272.05
  600.85  3282.6     627 3297.48  636.91 3297.85   684.5 3326.58   694.6 3337.04
   708.1 3346.28   721.6 3348.58   738.5 3348.05     786 3370.61   812.9  3377.6
   836.6 3389.44   853.5 3390.88   948.6 3435.72   968.4 3439.09   974.5 3442.41
#Mann= 5 ,-1 , 0
       0      .1       0     502    .045       0   539.5      .1       0
  600.85     .06       0  636.91    .055       0
Bank Sta=502,539.5
XS Rating Curve= 0 ,0
Exp/Cntr=0.3,0.1

Type RM Length L Ch R = 1 ,6619    ,258.1,258.1,258.1
XS GIS Cut Line= 2
2101355.79724367 382534.994909052101064.91684349383402.395021305
#Sta/Elev= 30
       0 3417.44    20.1 3409.25    73.1 3395.02    97.9 3386.04   135.4 3380.15
   183.4 3360.07   221.9 3339.38   322.2 3292.89   332.6  3290.7   405.3 3263.13
   436.4 3259.65   445.1 3255.93   455.4 3254.19   471.1 3255.86   484.9 3261.44
   526.4 3260.93   547.1 3266.46  573.34 3269.73   609.4 3277.84   626.7 3286.88
     651 3287.99   720.2 3318.05   748.3  3332.8  762.97 3343.78   799.7 3345.31
   815.7 3356.95   877.9 3379.02   893.2 3379.61   903.6  3389.5   914.9 3395.09
#Mann= 5 ,-1 , 0
       0      .1       0   445.1    .045       0   471.1      .1       0
  573.34     .06       0  762.97    .055       0
Bank Sta=445.1,471.1
XS Rating Curve= 0 ,0
Exp/Cntr=0.3,0.1

Type RM Length L Ch R = 1 ,6361    ,300,300,300
XS GIS Cut Line= 3
     2101080.966      382424.266     2100976.487       382866.31
     2100884.276      383323.859
#Sta/Elev= 30
       0 3381.41   104.1 3357.54   265.9 3306.18     302 3291.63   336.7 3266.16
   356.5 3257.73   370.1 3255.12   441.2 3251.81   447.9 3247.31   454.6 3245.06
   471.4  3247.5   481.4 3248.85   494.8  3255.9   548.4  3257.6  615.66 3264.33
   635.7 3267.96   672.2 3278.83   692.3 3281.85   705.7 3289.63   725.7 3292.07
  741.51 3300.15   759.2 3304.14   773.2 3310.83     786  3322.6   794.5 3327.19
   826.2 3329.03   864.1 3350.06   894.7 3362.84   913.2  3365.4     921 3369.53
#Mann= 5 ,-1 , 0
       0      .1       0   447.9    .045       0   471.4      .1       0
  615.66     .06       0  741.51    .055       0
Bank Sta=447.9,471.4
XS Rating Curve= 0 ,0
Exp/Cntr=0.3,0.1

Type RM Length L Ch R = 1 ,6061    ,300,300,300
XS GIS Cut Line= 3
     2100708.136      382404.877     2100687.025      382875.884
     2100659.945      383327.703
#Sta/Elev= 30
       0 3371.24    51.8 3354.02     147 3309.34     216 3280.49   298.1 3254.08
   324.4 3242.47   383.5 3240.91   399.9 3237.28   419.6 3240.93     436 3239.64
   448.8  3235.2   468.9 3233.26   483.9 3235.42   501.8 3248.93   551.1 3255.18
  563.32 3253.12   570.8 3250.06   590.5 3260.34   626.7 3271.28   652.9 3288.39
  679.72 3292.87   705.5    3311   738.4  3312.5   761.4 3330.49   780.6 3333.97
     798 3344.77   865.4 3365.84   892.9 3367.33   902.7 3374.59   924.1 3383.98
#Mann= 5 ,-1 , 0
       0      .1       0   448.8    .045       0   483.9      .1       0
  563.32     .06       0  679.72    .055       0
#XS Ineff= 2 , 0
          420.69 3244.43
Permanent Ineff=
       F       F
Bank Sta=448.8,483.9
XS Rating Curve= 0 ,0
Exp/Cntr=0.3,0.1

Type RM Length L Ch R = 1 ,5761    ,300,300,300
XS GIS Cut Line= 3
     2100510.508      382343.719     2100409.921      382783.847
     2100298.633      383245.511
#Sta/Elev= 30
       0 3376.87   102.4 3338.39   115.8 3330.48   139.4 3321.76   220.3 3284.09
   277.4 3261.17   317.7 3249.71   357.3 3244.36   391.8 3235.12   432.2 3231.49
   441.9 3226.41     449 3224.63   477.6 3226.76   496.2 3227.01   546.9 3236.52
     557 3241.63   604.2 3255.87   617.7 3258.13  632.57 3264.46   651.1 3272.43
   670.7 3281.34     692 3294.72   722.4 3297.25   739.2 3309.87   763.1 3322.04
   806.8 3342.84   850.6 3360.47   870.8 3362.91   882.4 3367.56   926.4 3377.12
#Mann= 5 ,-1 , 0
       0      .1       0   441.9    .045       0   477.6      .1       0
  632.57     .06       0   651.1    .055       0
Bank Sta=441.9,477.6
XS Rating Curve= 0 ,0
Exp/Cntr=0.3,0.1

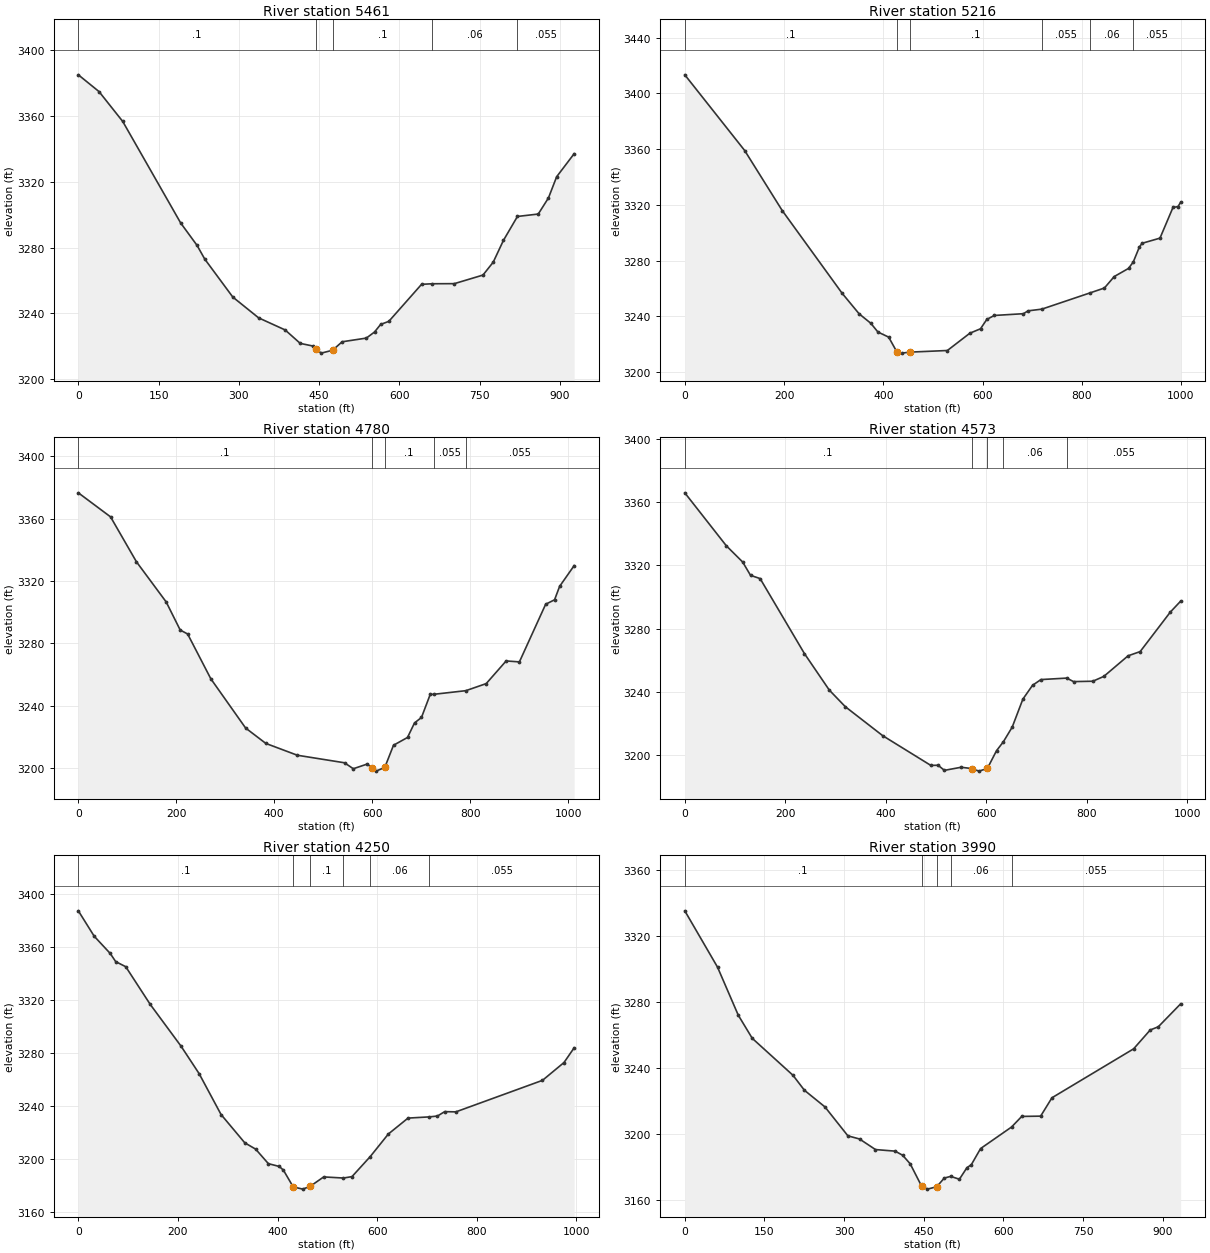
Type RM Length L Ch R = 1 ,5461    ,244.6,244.6,244.6
XS GIS Cut Line= 3
     2100417.671      382307.068     2100153.885      382676.373
     2099911.062       383081.82
#Sta/Elev= 30
       0 3385.12    38.7 3374.91      83 3356.72   191.2 3294.95   221.8 3281.31
   236.2 3272.97   288.6 3249.85   336.9 3237.18   386.4 3229.83   414.6 3221.65
   438.6 3220.02   444.3 3218.26   453.8 3215.72     475 3217.47   492.9 3222.63
   538.1 3224.87   553.4 3228.56   564.8 3233.19   580.1 3235.05   641.3  3257.6
  661.22 3257.95   702.5 3258.01     756 3263.23   775.2  3271.1   794.2 3284.31
  820.42 3298.91   859.3 3300.38   878.4  3310.2   893.7 3323.08   926.4 3337.12
#Mann= 5 ,-1 , 0
       0      .1       0   444.3    .045       0     475      .1       0
  661.22     .06       0  820.42    .055       0
Bank Sta=444.3,475
XS Rating Curve= 0 ,0
Exp/Cntr=0.3,0.1

Type RM Length L Ch R = 1 ,5216    ,436,436,436
XS GIS Cut Line= 3
2100185.72428258382141.9132871822099831.95082289382759.051433515
2099855.53572021383046.001017478
#Sta/Elev= 30
       0 3413.28   120.7    3359   196.4 3315.93   317.1 3256.64   351.4 3241.89
   374.8 3235.17   389.2 3228.88   410.9  3225.2     427 3214.85   437.3 3213.73
   453.5 3214.45   529.2 3215.61   574.5 3228.01     596 3231.19   608.6 3237.87
   623.7 3240.74   682.5    3242   691.8 3244.05  719.48 3245.26  817.25 3256.98
   845.7 3260.42   865.5 3268.64   894.3 3274.47   903.9 3279.11   915.8  3289.5
   921.4 3292.46   957.7 3296.19   983.9 3318.19   993.9 3318.78   999.3 3321.84
#Mann= 6 ,-1 , 0
       0      .1       0     427    .045       0   453.5      .1       0
  719.48    .055       0  817.25     .06       0   903.9    .055       0
Bank Sta=427,453.5
XS Rating Curve= 0 ,0
Exp/Cntr=0.3,0.1

Type RM Length L Ch R = 1 ,4780    ,202.8,207,210.5
XS GIS Cut Line= 2
2099857.92362887 382042.438121062099458.29064664382972.731292814
#Sta/Elev= 30
       0 3376.64    65.8 3361.22   118.7 3332.39   179.4 3306.64     208 3288.64
   223.2 3286.08   270.6 3257.33   341.6 3225.77   382.9 3215.89   447.2 3208.31
   543.6 3203.47   561.5 3199.65   590.1 3202.68   599.3 3200.22   607.9 3198.12
   625.8 3200.49   643.6 3214.72   672.2 3219.71   686.5 3229.04   700.7 3232.53
   718.6 3247.35  725.653247.389  791.283249.727   832.9 3254.26   873.6  3268.8
   900.7 3268.19   954.3 3305.16   972.5 3308.03   982.8 3316.63  1012.5 3329.96
#Mann= 5 ,-1 , 0
       0      .1       0   599.3    .045       0   625.8      .1       0
  725.65    .055       0  791.28    .055       0
Bank Sta=599.3,625.8
XS Rating Curve= 0 ,0
Exp/Cntr=0.3,0.1

Type RM Length L Ch R = 1 ,4573    ,322.7,322.7,322.7
XS GIS Cut Line= 3
2099700.69098013 381992.647782292099550.00969174382370.006139283
2099190.99514377 382825.98082065
#Sta/Elev= 30
       0 3365.89    82.7  3332.4   115.1 3322.18   130.8 3313.75   149.9 3311.69
   238.2 3264.22   287.6 3241.19   319.4 3230.72   393.6 3212.45   489.6 3193.61
   504.1  3193.7   516.6 3190.48     550 3192.44   570.9 3191.62   585.4 3189.99
   602.1 3191.68   620.4 3202.93  633.97 3208.55   651.6 3217.84   672.8 3235.51
     692 3244.23   708.7 3247.86  760.07 3248.79   773.6 3246.57     812 3246.81
   833.9 3249.87   882.1 3262.87   906.2 3265.55   966.2 3290.51   986.7 3297.41
#Mann= 5 ,-1 , 0
       0      .1       0   570.9    .045       0   602.1      .1       0
  633.97     .06       0  760.07    .055       0
Bank Sta=570.9,602.1
XS Rating Curve= 0 ,0
Exp/Cntr=0.3,0.1

Type RM Length L Ch R = 1 ,4250    ,260.8,260.8,260.8
XS GIS Cut Line= 2
2099504.15016919381838.0356776892099067.82956892382732.951503475
#Sta/Elev= 30
       0  3387.3    31.9  3368.1    64.1 3355.08      75 3348.94    95.2 3345.09
   144.4 3316.61   206.4 3284.99   242.5 3264.36   286.6 3233.44   334.2 3212.09
   356.1 3207.29   381.6 3196.33   403.5 3194.23   411.8 3191.44   431.4  3178.8
   450.7  3177.1   465.7 3179.26   492.7 3186.32  532.34 3185.48   549.5 3186.55
   586.2 3201.71   622.5 3218.73     662 3230.75  704.62 3231.66   721.1 3232.31
   735.6 3235.62   758.1 3235.46     932 3259.26   975.2 3272.72   995.6 3283.84
#Mann= 6 ,-1 , 0
       0      .1       0   431.4    .045       0   465.7      .1       0
  532.34    .055       0   586.2     .06       0  704.62    .055       0
Bank Sta=431.4,465.7
XS Rating Curve= 0 ,0
Exp/Cntr=0.3,0.1

Type RM Length L Ch R = 1 ,3990    ,382.8,382.8,382.8
XS GIS Cut Line= 2
2099240.78548254381737.1447280762098879.15039042382597.993479967
#Sta/Elev= 30
       0 3335.03    61.6 3300.98   100.7  3271.9     127 3257.92   203.7 3235.56
   225.3 3226.48   263.9 3216.43   307.1 3198.93     329 3197.02   359.1 3190.62
   396.1 3189.67   410.3 3187.17   424.5 3181.98   445.9  3168.5   456.8 3166.69
   474.4 3168.11   488.6 3173.38  500.75  3174.4   517.1 3172.67   531.3 3179.67
   539.5 3181.43     557 3191.23  615.29 3204.25   634.5 3210.67   670.1 3210.84
   691.4 3221.95   845.2 3251.55   876.5 3262.97   891.7  3264.9   933.7 3278.75
#Mann= 5 ,-1 , 0
       0      .1       0   445.9    .045       0   474.4      .1       0
  500.75     .06       0  615.29    .055       0
Bank Sta=445.9,474.4
XS Rating Curve= 0 ,0
Exp/Cntr=0.3,0.1

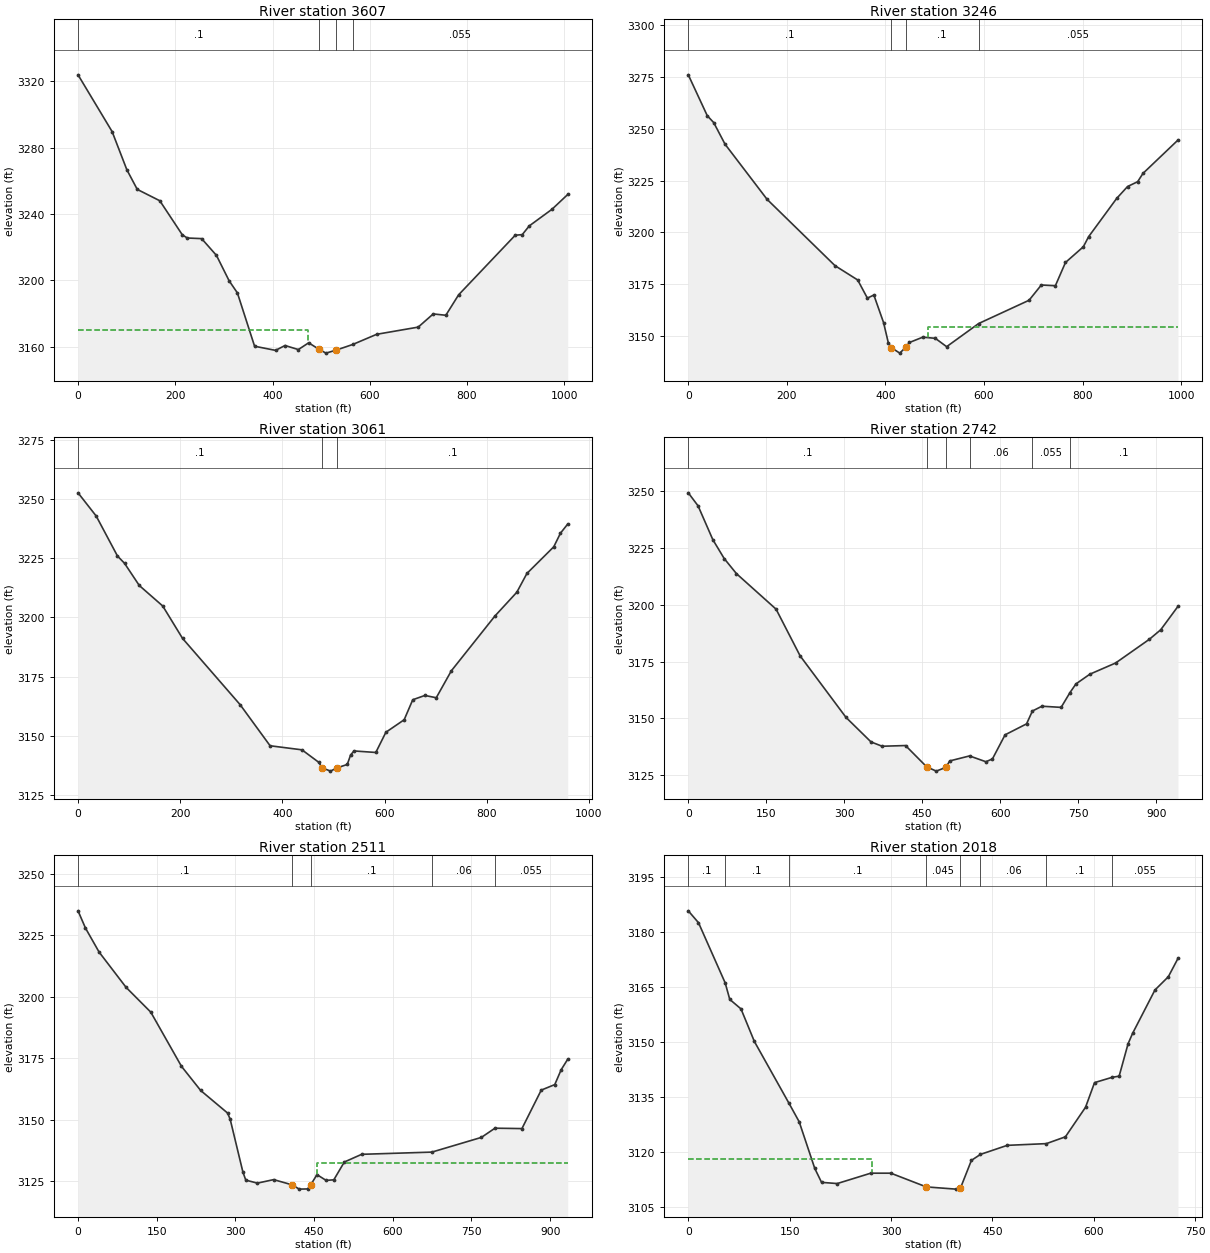
Type RM Length L Ch R = 1 ,3607    ,360.5,360.5,360.5
XS GIS Cut Line= 4
2099086.17337794381642.8051388282098966.93861931381877.343839876
2098583.02890195382127.6058057982098442.82979015382376.557499648
#Sta/Elev= 30
       0 3323.86    70.1 3289.65   100.4 3266.65   121.8 3254.81   168.2 3247.95
   214.5 3227.42   224.7  3225.5   254.2 3225.13   284.7 3215.02   310.7 3199.74
   327.8 3192.38   363.1 3160.27   406.2 3157.77   425.7  3160.7   453.1 3158.26
   474.3 3162.33   495.7  3158.4   509.9 3156.11   531.5 3157.99  564.92 3161.32
   614.2 3167.46   699.6 3171.79   730.5 3179.74   756.4 3178.93   782.7 3191.25
   899.1 3227.17   913.6 3227.55     928  3232.8   974.7 3242.81  1007.1 3251.73
#Mann= 4 ,-1 , 0
       0      .1       0   495.7    .045       0   531.5      .1       0
  564.92    .055       0
#XS Ineff= 2 , 0
           473.8 3170.12
Permanent Ineff=
       F       F
Bank Sta=495.7,531.5
XS Rating Curve= 0 ,0
Exp/Cntr=0.3,0.1

Type RM Length L Ch R = 1 ,3246    ,185.5,185.5,185.5
XS GIS Cut Line= 3
2098526.68720281381391.2329008322098539.78992354382041.127848987
2098407.45244418382358.213690627
#Sta/Elev= 30
       0 3275.84    38.5 3256.18    51.6 3252.86    74.6 3242.46   159.9 3215.94
   297.7 3184.04   343.7 3177.16   363.4 3168.42   376.5 3169.92   396.2 3156.67
     406  3146.8   412.2 3144.57   429.1 3141.97   440.8  3144.7   448.7 3147.09
   475.8 3149.65   501.2 3149.09   524.2 3145.07  589.17 3156.21   691.4  3167.4
   716.3 3174.74   744.8 3174.38   765.3 3185.57   801.6 3193.14   812.3 3197.99
   869.2 3216.39   891.3 3222.11   911.8 3224.44   922.5 3228.41   993.6 3244.47
#Mann= 4 ,-1 , 0
       0      .1       0   412.2    .045       0   440.8      .1       0
  589.17    .055       0
#XS Ineff= 2 , 0
                          486.35         3154.47
Permanent Ineff=
       F       F
Bank Sta=412.2,440.8
XS Rating Curve= 0 ,0
Exp/Cntr=0.3,0.1

Type RM Length L Ch R = 1 ,3061    ,318.4,318.4,318.4
XS GIS Cut Line= 3
     2098351.673      381398.493     2098366.115       381888.63
     2098340.165      382355.997
#Sta/Elev= 30
       0 3252.63    35.6 3242.82    77.2 3225.95      91 3222.88   119.9  3213.5
   165.8 3204.84   204.6 3191.15   317.3 3163.17   375.9 3145.83   438.3 3144.11
   471.1 3138.85   477.6 3136.56   494.1 3135.12   506.8  3136.5   526.9 3137.93
   533.5 3141.95   540.1 3143.64   582.8    3143   602.5 3151.53   638.3 3156.81
   655.1 3165.26   678.8 3167.07   701.1 3166.11   730.6 3177.47   816.1 3200.66
   858.8 3210.66   878.5 3218.58   931.1 3229.85   944.2  3235.6   958.4 3239.45
#Mann= 3 ,-1 , 0
       0      .1       0   477.6    .045       0   506.8      .1       0
Bank Sta=477.6,506.8
XS Rating Curve= 0 ,0
Exp/Cntr=0.3,0.1

Type RM Length L Ch R = 1 ,2742    ,231.2,231.2,231.2
XS GIS Cut Line= 2
 2098300.2106059381380.2219423292097866.68848796382216.531401198
#Sta/Elev= 30
       0 3249.26    18.8 3243.53    47.2 3228.65    69.1 3220.33    92.7 3213.68
   168.9 3198.05   215.1 3177.51   303.4 3150.41   351.5 3139.62   372.9 3137.72
   417.9 3138.03   458.5 3128.67     477 3126.77   495.5 3128.42   502.9 3131.26
  541.03 3133.46   572.5  3130.9   585.1 3132.15   609.4 3142.75   650.7 3147.57
  661.97 3153.23   680.3 3155.34   717.2 3154.83  734.24 3161.35   745.7 3165.15
   772.5 3169.44     822 3174.36   886.9 3184.79   908.8 3188.99     942  3199.3
#Mann= 6 ,-1 , 0
       0      .1       0   458.5    .045       0   495.5      .1       0
  541.03     .06       0  661.97    .055       0  734.24      .1       0
Bank Sta=458.5,495.5
XS Rating Curve= 0 ,0
Exp/Cntr=0.3,0.1

Type RM Length L Ch R = 1 ,2511    ,493.5,493.5,493.5
XS GIS Cut Line= 2
 2098082.5049701381302.1343998762097659.28709056382134.157166163
#Sta/Elev= 30
       0 3235.01    14.2 3227.98    40.1 3218.23    91.6 3203.84   138.7 3193.74
   197.2 3171.67   233.8 3161.83   285.1 3152.64     290 3150.14   314.3  3128.6
   319.8 3125.32   341.9 3124.09   372.9 3125.52   408.2 3123.39   421.7 3121.65
   437.6 3121.73   443.7 3123.45   455.5 3127.55   472.9 3125.21   487.6 3125.44
   507.6 3132.69   540.7 3135.83  674.52 3136.73   768.9 3142.72  794.78 3146.47
   846.2 3146.31     883 3161.98   908.8 3164.23     921 3170.29   933.5 3174.57
#Mann= 5 ,-1 , 0
       0      .1       0   408.2    .045       0   443.7      .1       0
  674.52     .06       0  794.78    .055       0
#XS Ineff= 2 , 0
                          454.61         3132.19
Permanent Ineff=
       F       F
Bank Sta=408.2,443.7
XS Rating Curve= 0 ,0
Exp/Cntr=0.3,0.1

Type RM Length L Ch R = 1 ,2018    ,245.9,245.9,245.9
XS GIS Cut Line= 2
2097470.60791206381414.8177981442097568.87831753 382132.84689409
#Sta/Elev= 30
       0 3185.75    15.1 3182.51    54.6 3166.08    61.4 3161.57      78 3158.98
    97.8 3150.09  148.43 3133.42   164.1 3128.18   187.2 3115.43   197.2 3111.64
   220.4 3111.31     270 3114.14   299.8 3114.14   352.2  3110.4   395.9 3109.79
   402.8 3110.08     419 3117.64  432.41 3119.27     472 3121.74  529.94 3122.21
   558.1 3124.07   587.9 3132.14   601.2 3138.86  627.47 3140.32   637.6 3140.62
   650.8 3149.45   657.5  3152.3   690.6 3164.14   710.4 3167.76   724.7 3172.77
#Mann= 8 ,-1 , 0
       0      .1       0    54.6      .1       0  148.43      .1       0
   352.2    .045       0   402.8      .1       0  432.41     .06       0
  529.94      .1       0  627.47    .055       0
#XS Ineff= 2 , 0
          272.31    3118
Permanent Ineff=
       F       F
Bank Sta=352.2,402.8
XS Rating Curve= 0 ,0
Exp/Cntr=0.3,0.1