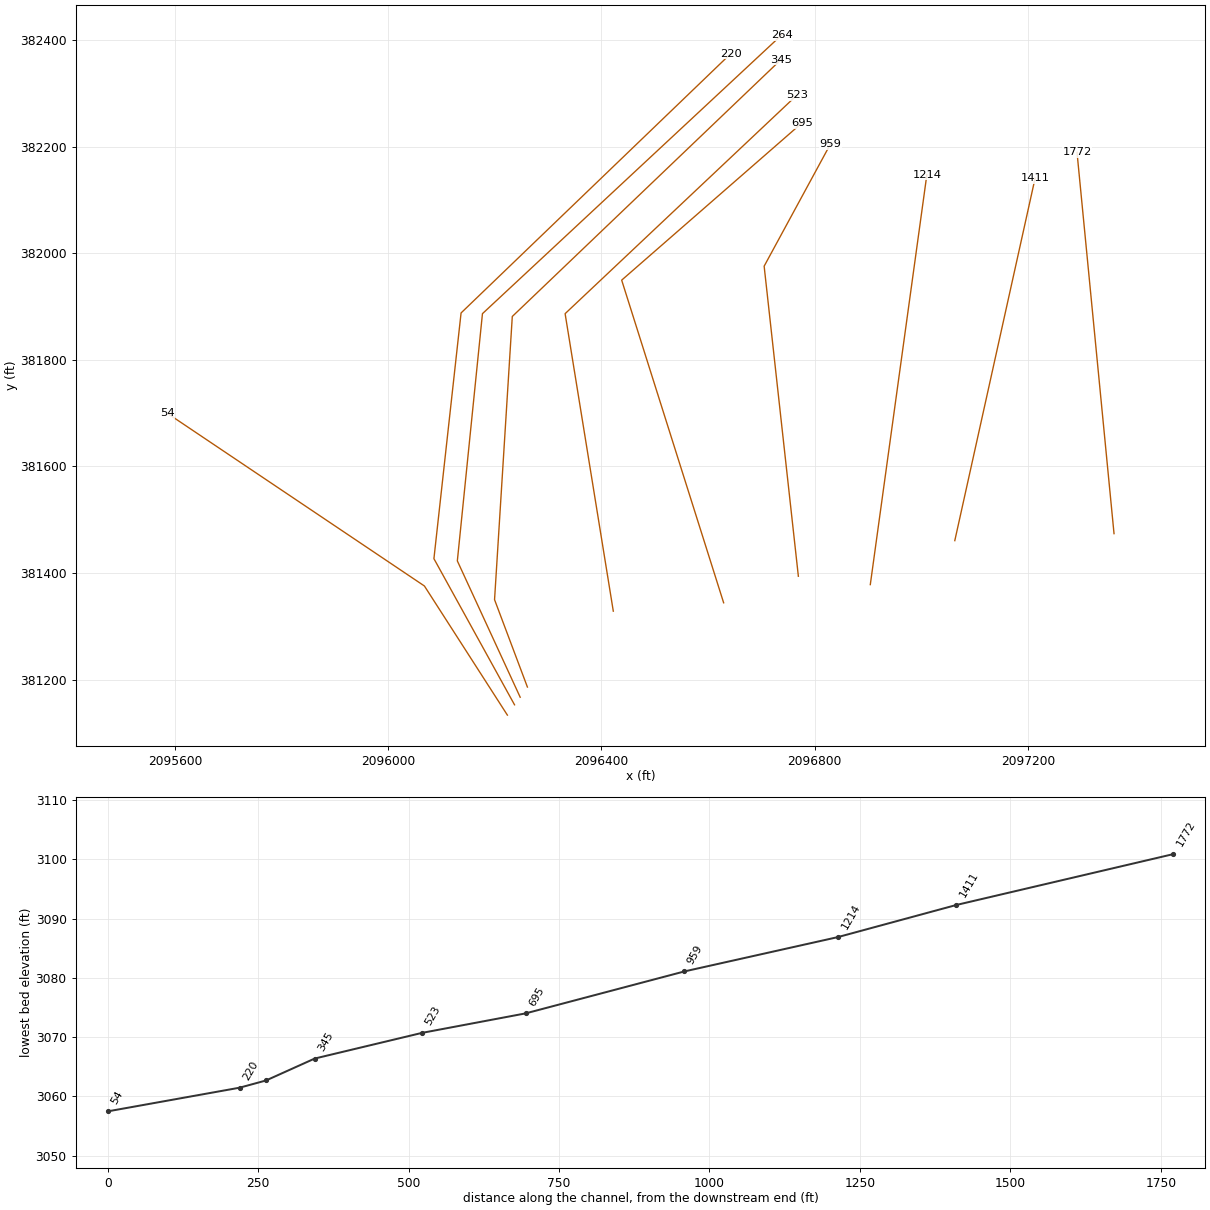
HEC-RAS study OLFLDBR.prj: OLFLDBR

--- OLFLDBR.g01 (geometry) --- (continued)

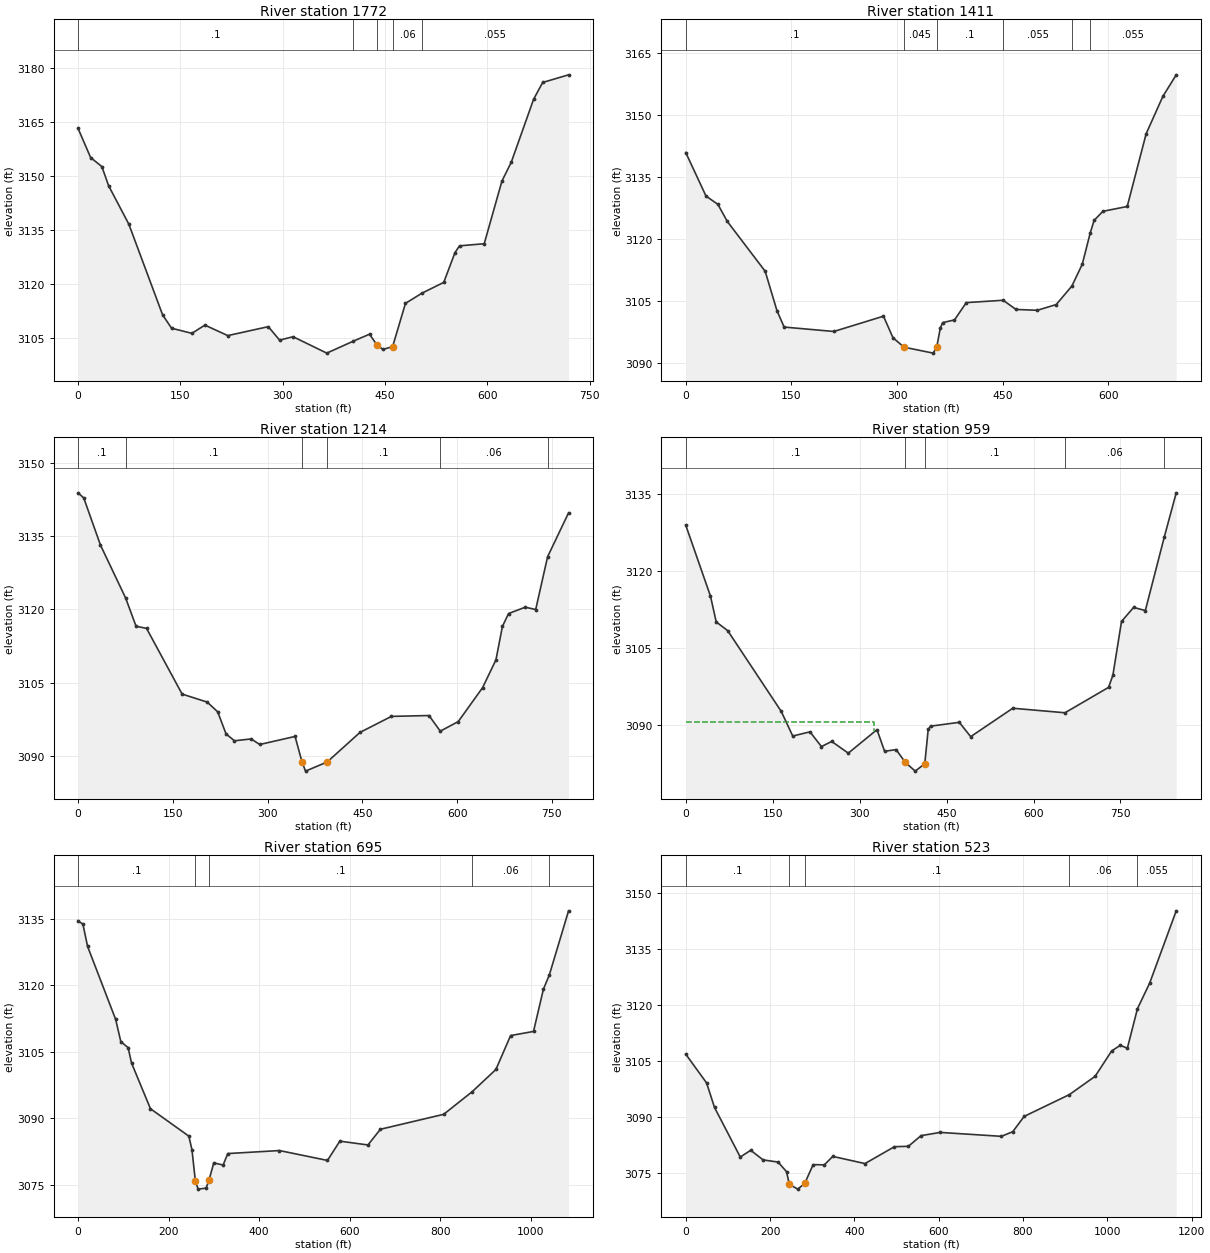
Type RM Length L Ch R = 1 ,1772    ,360.9,360.9,360.9
XS GIS Cut Line= 2
2097361.85533001381473.7800414252097292.41091015382189.188593224
#Sta/Elev= 30
       0 3163.21    18.4 3155.13    34.9 3152.62    44.7 3147.34    74.4 3136.65
   123.9  3111.5     137  3107.8   166.7 3106.38   185.9 3108.66   219.4 3105.75
   278.8 3108.23   295.3 3104.49   315.1 3105.44   364.5 3100.89  403.51 3104.22
   427.1 3106.14   438.3 3103.09   446.9 3101.91     461 3102.71   479.8 3114.69
  504.18 3117.54   535.9 3120.51   552.4 3128.78     559 3130.64   595.2 3131.23
   621.2 3148.62   634.8 3153.81   667.7 3171.35   680.9 3175.95   718.8 3178.07
#Mann= 5 ,-1 , 0
       0      .1       0  403.51     .06       0   438.3    .045       0
     461     .06       0  504.18    .055       0
Bank Sta=438.3,461
XS Rating Curve= 0 ,0
Exp/Cntr=0.3,0.1

Type RM Length L Ch R = 1 ,1411    ,196.9,196.9,196.9
XS GIS Cut Line= 2
2097063.11329739381460.6773206962097213.79458578382140.708526527
#Sta/Elev= 30
       0 3140.95    28.8 3130.38    45.6 3128.39      59 3124.24   112.8 3112.15
   129.6 3102.56   139.7 3098.62   210.3 3097.55   280.8 3101.26   294.3 3096.02
     310 3093.74   351.4  3092.3   356.4 3093.75   361.5 3098.38   364.8  3099.7
   381.6 3100.35   398.4 3104.55  450.69 3105.12     469 3102.89   499.2 3102.69
   526.1 3104.08   548.4 3108.59   563.1 3113.87  574.37 3121.44   579.9 3124.49
   592.3 3126.69   626.9 3127.86   653.8 3145.51   677.6 3154.59   696.5 3159.79
#Mann= 6 ,-1 , 0
       0      .1       0     310    .045       0   356.4      .1       0
  450.69    .055       0   548.4     .06       0  574.37    .055       0
Bank Sta=310,356.4
XS Rating Curve= 0 ,0
Exp/Cntr=0.3,0.1

Type RM Length L Ch R = 1 ,1214    ,255,255,255
XS GIS Cut Line= 2
2096904.57037657381378.1301801032097010.70241448382147.259886892
#Sta/Elev= 30
       0 3143.84       9 3142.79    35.5 3133.13   75.24 3122.33    91.8 3116.53
   108.4  3116.1   164.7 3102.65   204.4 3101.01     221 3099.02   234.2 3094.51
   247.5 3093.09     274 3093.47   287.6 3092.33   343.5 3093.98   354.5 3088.74
   360.1 3086.88   394.4 3088.76   446.2  3094.8   495.9 3098.08   555.5 3098.26
  573.35 3095.06   601.8 3097.02   640.3 3103.96   661.5 3109.66   671.7 3116.49
   681.4 3119.13   707.8 3120.43   724.4 3119.96  743.24 3130.76   776.4 3139.74
#Mann= 6 ,-1 , 0
       0      .1       0   75.24      .1       0   354.5    .045       0
   394.4      .1       0  573.35     .06       0  743.24    .055       0
Bank Sta=354.5,394.4
XS Rating Curve= 0 ,0
Exp/Cntr=0.3,0.1

Type RM Length L Ch R = 1 ,959     ,263.9,263.9,263.9
XS GIS Cut Line= 3
2096769.61235307381393.8534449782096705.40902149381975.614245343
2096829.88486842382204.911858099
#Sta/Elev= 30
       0 3128.97    42.7 3115.14    52.6 3110.13    72.4 3108.43   164.8 3092.71
   184.6 3087.92   214.3 3088.74   234.1 3085.87   251.8 3086.87   280.4 3084.59
   329.9 3089.16   343.1 3084.95   362.9 3085.28     379 3082.77   395.9 3081.09
   412.4 3082.53   412.4 3082.56   418.3 3089.21   422.3 3089.84   471.9 3090.59
   491.6  3087.8   564.2 3093.33  654.27 3092.45   729.4 3097.39   736.9 3099.74
   751.8 3110.22   772.6 3112.95   792.9 3112.35  825.61 3126.66   846.2 3135.26
#Mann= 5 ,-1 , 0
       0      .1       0     379    .045       0   412.4      .1       0
  654.27     .06       0  825.61    .055       0
#XS Ineff= 2 , 0
          324.86 3090.62
Permanent Ineff=
       F       F
Bank Sta=379,412.4
XS Rating Curve= 0 ,0
Exp/Cntr=0.3,0.1

Type RM Length L Ch R = 1 ,695     ,172.2,172.2,172.2
XS GIS Cut Line= 3
2096629.41324127381344.0631062082096438.11351862381949.408803885
2096776.16371343382244.220020286
#Sta/Elev= 30
       0 3134.51    10.7 3133.77      21 3128.75      83 3112.29    94.5 3107.25
   110.5 3105.93   118.1 3102.45   159.9 3092.14   244.7 3085.96   251.6 3082.87
   259.2 3075.74   265.3 3074.01   282.8 3074.24   289.4 3076.11   299.7 3079.92
   320.4 3079.45   330.7 3082.03   444.9 3082.71   550.9 3080.48   578.2 3084.83
   640.3 3083.97   667.8 3087.51   807.6 3090.88   870.6 3095.99   922.9 3100.99
   955.4 3108.64    1006 3109.57  1027.8 3119.07 1040.99 3122.32  1083.4 3136.77
#Mann= 5 ,-1 , 0
       0      .1       0   259.2    .045       0   289.4      .1       0
   870.6     .06       0 1040.99    .055       0
Bank Sta=259.2,289.4
XS Rating Curve= 0 ,0
Exp/Cntr=0.3,0.1

Type RM Length L Ch R = 1 ,523     ,178.3,178.3,178.3
XS GIS Cut Line= 3
2096422.39025375381328.3398413332096331.98148072381886.515744386
2096766.99180892382296.630903201
#Sta/Elev= 30
       0 3106.89    49.5 3099.17    68.2 3092.62   129.3 3079.32     154 3081.13
   183.5 3078.55     219 3077.97     239 3075.41   245.7 3071.99   265.6 3070.72
   282.2 3072.25   302.1 3077.28   328.7 3077.23   348.7 3079.49   425.1 3077.57
   494.9 3082.09   528.1  3082.2     558 3085.05   603.5 3085.92   748.6 3084.87
   775.6 3086.11   802.7 3090.22   909.9 3096.05   970.9 3100.95  1010.1 3107.74
  1030.5 3109.26  1047.4 3108.48 1071.31 3119.07  1100.3 3125.93  1163.3  3145.3
#Mann= 5 ,-1 , 0
       0      .1       0   245.7    .045       0   282.2      .1       0
   909.9     .06       0 1071.31    .055       0
Bank Sta=245.7,282.2
XS Rating Curve= 0 ,0
Exp/Cntr=0.3,0.1

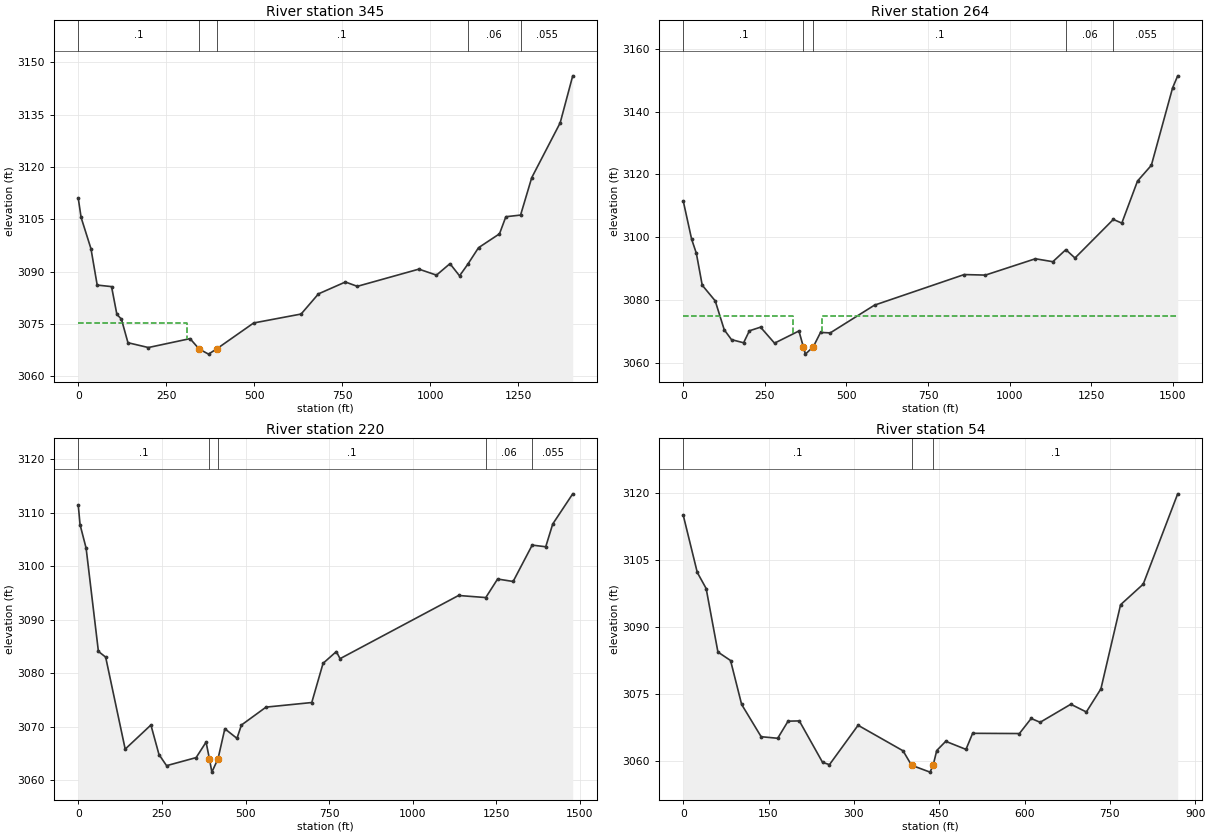
Type RM Length L Ch R = 1 ,345     ,80.9,80.9,80.9
XS GIS Cut Line= 4
2096261.23072597381185.9706403832096199.59302429381349.926926874
 2096232.8773832381881.2439154262096737.07378301382363.250742629
#Sta/Elev= 30
       0 3111.05     8.1 3105.55    36.1  3096.6    53.8 3086.18    94.6 3085.74
   109.7 3077.78   122.6 3076.42   141.2 3069.66   199.2 3068.28   317.6 3070.83
   343.9 3067.82   370.2 3066.39   393.2 3067.88   498.4 3075.32   633.2 3077.88
   682.5 3083.66     759 3087.06   792.9 3085.82   967.9 3090.75  1017.9 3089.03
  1056.2 3092.32  1083.4 3088.83 1106.45 3092.09  1137.3 3096.89  1196.9 3100.87
    1215 3105.77 1256.81 3106.24  1288.5 3116.96  1369.3 3132.67    1405 3146.15
#Mann= 5 ,-1 , 0
       0      .1       0   343.9    .045       0   393.2      .1       0
 1106.45     .06       0 1256.81    .055       0
#XS Ineff= 2 , 0
          309.37 3075.24
Permanent Ineff=
       F       F
Bank Sta=343.9,393.2
XS Rating Curve= 0 ,0
Exp/Cntr=0.3,0.1

Type RM Length L Ch R = 1 ,264     ,44,44,44
XS GIS Cut Line= 4
2096247.69050599 381166.869428012096129.77536079381422.654235456
2096176.88948223381886.5157443862096738.16582332 382409.31430147
#Sta/Elev= 30
       0 3111.54    25.7 3099.35    40.2 3094.84    58.2 3084.67      98 3079.67
   125.7 3070.44   147.9 3067.31     185 3066.31   202.7 3070.13   236.9 3071.29
   279.7 3066.19   354.5 3070.07  368.34 3064.89   374.5 3062.69   398.8  3065.1
   420.7 3069.61   450.4 3069.46     586 3078.31   860.8 3088.06   925.8 3087.89
  1078.9  3093.1  1132.4 3092.16 1172.23    3096  1200.2 3093.34 1317.69 3105.64
  1343.7 3104.47  1391.8 3117.88  1434.2  3122.9  1499.2 3147.56  1514.9 3151.43
#Mann= 5 ,-1 , 0
       0      .1       0  368.34    .045       0   398.8      .1       0
 1172.23     .06       0 1317.69    .055       0
#XS Ineff= 2 , 0
          337.71    3075  423.91            3075
Permanent Ineff=
       F       F
Bank Sta=368.34,398.8
XS Rating Curve= 0 ,0
Exp/Cntr=0.3,0.1

Type RM Length L Ch R = 1 ,220     ,219,219,219
XS GIS Cut Line= 4
2096237.07540897 381152.650150822096085.82795364381426.836714227
 2096136.7829787381887.8583695122096642.28917967382373.953132366
#Sta/Elev= 30
       0 3111.42     5.4 3107.79    23.5 3103.39    60.2 3084.07    81.9    3083
   140.3 3065.78   217.2 3070.29   241.3 3064.77     264 3062.68   352.4 3064.19
   382.1 3067.09  392.31 3063.91   399.4 3061.47   417.9 3063.99   438.2 3069.59
   474.5 3067.79   487.7 3070.28   561.4 3073.64   698.1  3074.5   731.9 3081.84
   771.6 3084.04   782.7 3082.71    1137 3094.54 1218.33 3094.15  1253.7 3097.62
  1300.1 3097.16 1357.13 3103.97  1397.6 3103.66  1418.5 3107.92  1478.3 3113.57
#Mann= 5 ,-1 , 0
       0      .1       0  392.31    .045       0   417.9      .1       0
 1218.33     .06       0 1357.13    .055       0
Bank Sta=392.31,417.9
XS Rating Curve= 0 ,0
Exp/Cntr=0.3,0.1

Type RM Length L Ch R = 1 ,54      ,54,54,54
XS GIS Cut Line= 3
2096223.65583131 381133.342755662096068.00160859381375.573883325
2095585.38141506381699.776761417
#Sta/Elev= 30
       0 3115.01    24.7 3102.19    40.3 3098.59      61 3084.37    83.2 3082.47
   102.7 3072.63     137 3065.41   166.1 3065.06   184.3 3068.89   204.1 3068.95
     245 3059.66   257.1 3059.16   307.4 3067.97   386.5 3062.25   401.4 3059.02
   433.9 3057.48  439.38 3059.04   445.7 3062.32   461.5 3064.38   497.1 3062.57
   508.8 3066.17     591 3066.12   611.7 3069.49   627.5 3068.64   681.4 3072.68
   708.7 3070.95   734.3 3076.12   768.9 3094.96   808.7 3099.57   869.3 3119.79
#Mann= 3 ,-1 , 0
       0      .1       0   401.4    .045       0  439.38      .1       0
Bank Sta=401.4,439.38
XS Rating Curve= 0 ,0
Exp/Cntr=0.3,0.1
LCMann Table=0

Chan Stop Cuts=-1
Use User Specified Reach Order=0
Composite Channel Slope=5